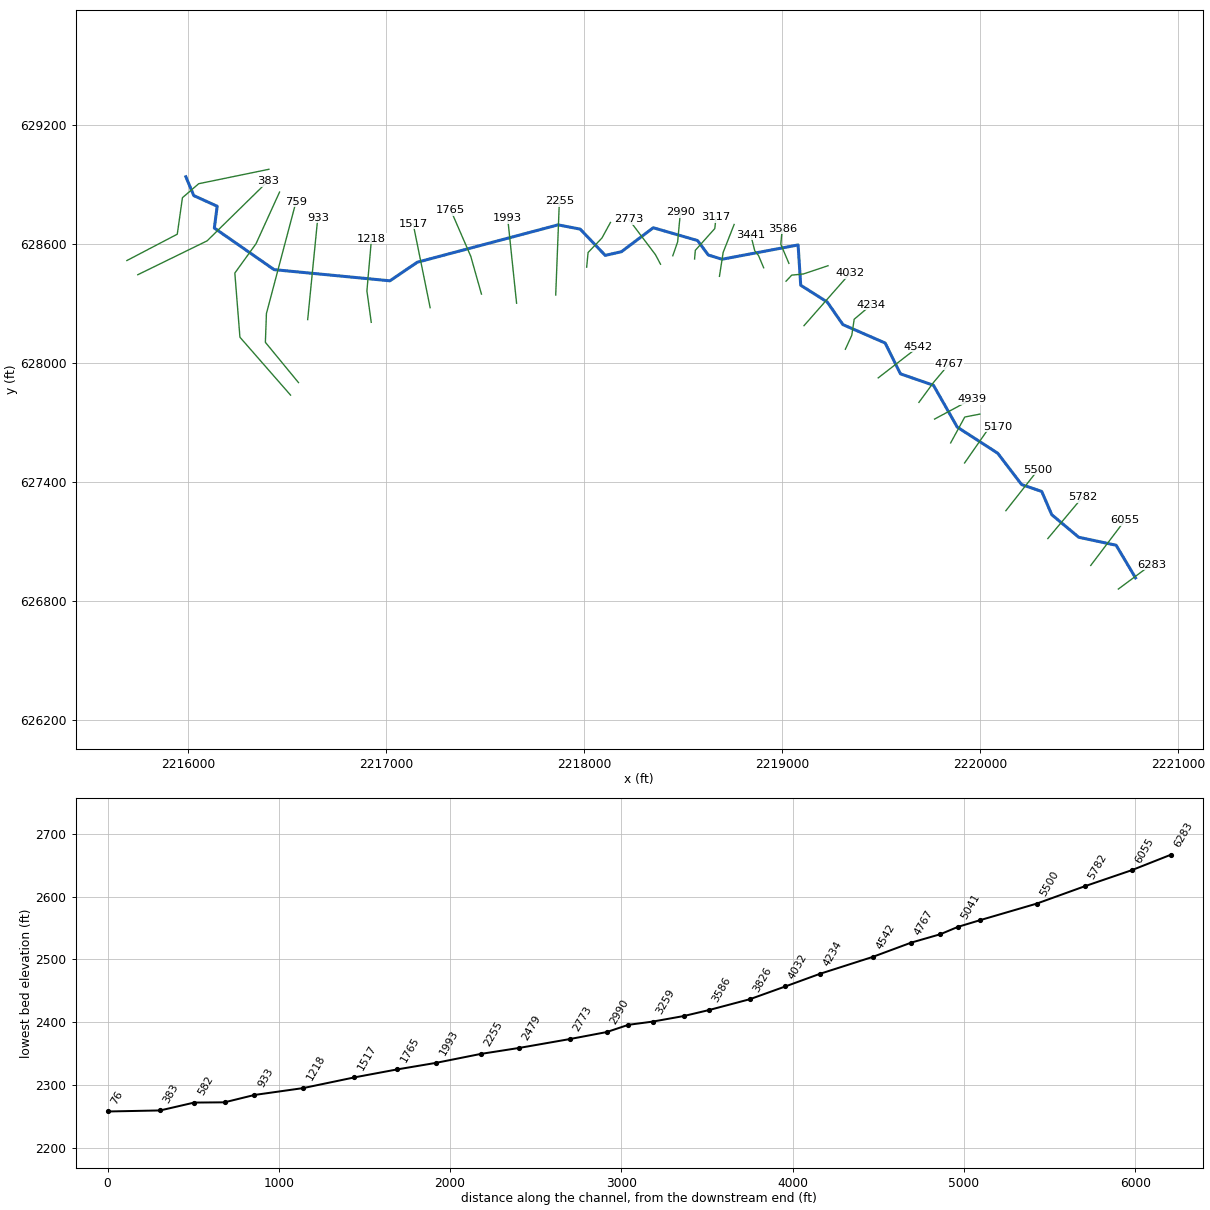
--- DRYRN3.prj (project) ---

Proj Title=DRYRN3
Current Plan=p01
Default Exp/Contr=0,0
English Units
Geom File=g01
Flow File=f01
Plan File=p01
BEGIN DESCRIPTION:
----------MODEL BY WOOD PLC 2022----------
AFH study
Randolph County, WV
HEC-RAS Version: RAS 6.2
Vertical Datum: NAVD88
Projection: NAD 1983 StatePlane West Virginia S FIPS 4702 (US Feet)
Terrain: 1-meter LIDAR (FEMA Region III 3DEP collected 2016-2018)
Land Use: 2019 NLCD
Hydrologic Method:
WV SIR2010-5033 regression equations
Additional Model Notes:
None
END DESCRIPTION:
DSS File=dss
DSS Export Rating Curves= 0
DSS Export Rating Curve Sorted= 0
DSS Export Volume Flow Curves= 0
DXF OffsetX= 0
DXF OffsetY= 0
DXF ScaleX= 0
DXF ScaleY= 0

--- DRYRN3.p01 (plan) ---

Plan Title=Floodplain
Program Version=6.20
Short Identifier=Floodplain
Geom File=g01
Flow File=f01
Subcritical Flow
K Sum by GR= 0
Std Step Tol= 0.01
Critical Tol= 0.01
Num of Std Step Trials= 20
Max Error Tol= 0.3
Flow Tol Ratio= 0.001
Split Flow NTrial= 30
Split Flow Tol= 0.02
Split Flow Ratio= 0.02
Log Output Level= 0
Friction Slope Method= 1
Unsteady Friction Slope Method= 2
Unsteady Bridges Friction Slope Method= 1
Parabolic Critical Depth
Global Vel Dist= 0 , 0 , 0
Global Log Level= 0
CheckData=True
Encroach Param=-1 ,0,0, 0
Computation Interval=0.1SEC
Output Interval=1SEC
Instantaneous Interval=Max Profile
Mapping Interval=1HOUR
Computation Time Step Use Courant=        0
Computation Time Step Use Time Series=    0
Computation Time Step Count To Double=0
Computation Time Step Max Doubling=0
Computation Time Step Max Halving=0
Computation Time Step Residence Courant=0
Run HTab= 0
Run UNet= 0
Run Sediment= 0
Run PostProcess= 0
Run WQNet= 0
Run RASMapper=-1
UNET Theta= 0
UNET Theta Warmup= 0
UNET ZTol= 0
UNET ZSATol= 0
UNET MxIter= 0
UNET Max Iter WO Improvement= 0
UNET MaxInSteps= 0
UNET DtIC= 0
UNET DtMin= 0
UNET MaxCRTS= 0
UNET WFStab= 0
UNET SFStab= 0
UNET WFX= 1
UNET SFX= 1
UNET Gravity=32.174
UNET 1D Methodology=Finite Difference
UNET DSS MLevel= 1
UNET Pardiso=0
UNET DZMax Abort= 0
UNET Use Existing IB Tables= 0
UNET Froude Reduction=False
UNET Froude Limit= 0
UNET Froude Power= 0
UNET D1 Cores= 0
UNET WindReference=Eulerian
UNET WindDragFormulation=Hsu (1988)
UNET D2 Coriolis=0
UNET D2 Cores= 0
UNET D2 Theta= 1
UNET D2 Theta Warmup= 1
UNET D2 Z Tol= 0.01
UNET D2 Volume Tol= 0.01
UNET D2 Max Iterations= 20
UNET D2 Equation= 0
UNET D2 RampUpFraction=0.1
UNET D2 TimeSlices= 1
UNET D2 Turbulence Formulation=Non-Conservative (original)
UNET D2 Eddy Viscosity=0.3
UNET D2 Transverse Eddy Viscosity=0.1
UNET D2 Smagorinsky Mixing=0
UNET D2 BCVolumeCheck=0
UNET D2 Cores=0
UNET D2 SolverType=PARDISO (Direct)
UNET D2 Minimum Iterations= 2147483647
UNET D2 Maximum Iterations= 2147483647
UNET D2 Restart Number= 10
UNET D2 Relaxation Coeff=1.3
UNET D2 SOR Precondition Iterations= 10
UNET D2 ILUT Maximum Fill= 8
UNET D2 ILUT Tolerance=1E-08
UNET D1D2 MaxIter= 0
UNET D1D2 ZTol=0.01
UNET D1D2 QTol=0.1
UNET D1D2 MinQTol=1
Write IC File= 0
Write IC File at Fixed DateTime=0
Write IC File at Sim End=0
Echo Input=False
Echo Parameters=False
Echo Output=False
Write Detailed= 0
HDF Write Warmup=0
HDF Write Time Slices=0
HDF Flush=0
HDF Compression= 1
HDF Chunk Size= 1
HDF Spatial Parts= 1
HDF Use Max Rows=0
HDF Fixed Rows= 1
Calibration Method= 0
Calibration Iterations= 20
Calibration Max Change=0.05
Calibration Tolerance=0.2
Calibration Maximum=1.5
Calibration Minimum=0.5
Calibration Optimization Method= 1
WQ AD Non Conservative
WQ ULTIMATE=-1
WQ Max Comp Step=1HOUR
WQ Output Interval=15MIN
WQ Output Selected Increments= 0
WQ Output face flow=0
WQ Output face velocity=0
WQ Output face area=0
WQ Output face dispersion=0
WQ Output cell volume=0
WQ Output cell surface area=0
WQ Output cell continuity=0
WQ Output cumulative cell continuity=0
WQ Output face conc=0
WQ Output face dconc_dx=0
WQ Output face courant=0
WQ Output face peclet=0
WQ Output face adv mass=0
WQ Output face disp mass=0
WQ Output cell mass=0
WQ Output cell source sink temp=0
WQ Output nsm pathways=0
WQ Output nsm derived pathways=0
WQ Create Restart=0
WQ Fixed Restart=0
WQ System Summary=0
WQ Write To DSS=0
Sorting and Armoring Iterations= 10
XS Update Threshold= 0.02
Bed Roughness Predictor= 0
Hydraulics Update Threshold= 0.02
Energy Slope Method= 1
Volume Change Method= 1
Sediment Retention Method= 0
Sediment TS Multiplier= 1
Warm Up Method= 0
XS Weighting Method= 0
Number of US Weighted Cross Sections= 1
Number of DS Weighted Cross Sections= 1
Upstream XS Weight=0
Main XS Weight=1
Downstream XS Weight=0
Number of DS XS's Weighted with US Boundary= 1
Upstream Boundary Weight= 1
Weight of XSs Associated with US Boundary= 0
Number of US XS's Weighted with DS Boundary= 1
Downstream Boundary Weight= 0.5
Weight of XSs Associated with DS Boundary= 0.5
Percentile Method= 0
Sediment Output Level= 3
Mass or Volume Output= 0
Output Increment Type= 1
Profile and TS Output Increment= 1
Transport Output Increment 1
XS Output Flag= 0
XS Output Increment= 10
Read HDF5 Sediment Hotstart= 0
Sediment Hotstart Type= 0
Write Gradation File= 0
Read Gradation Hotstart= 0
Write HDF5 File= 1
Write Binary Output= 1
Write DSS Sediment File= 0
DSS Sediment Output Type= 1
SV Curve= 0
Specific Gage Flag= 0
Subcell Erosion Methods= 0
Subcell Deposition Methods= 0
Advection Scheme= 1
Matrix Solver= 0
Implicit Weighting Factor= 1
Maximum Outer Loop Convergence Iterations= 5
Convergence Maximum Absolute= 0.001
Convergence RMSE= 0.0001
Grain Fractions Max Abs Error= 0.001
Max Subgrid Regions= 1
Max Subgrid Length Scale= 3.402823E+38
Initial Layer Thickness= 3.402823E+38
Min Layer Thickness= 3.402823E+38
Max Layer Thickness= 3.402823E+38
Number of Layers= 5

--- DRYRN3.f01 (steady flow) ---

Flow Title=Flow
Program Version=4.00
Number of Profiles=1
Profile Names=P100yr
River Rch & RM=DRYRN3,Main,6283
     381
River Rch & RM=DRYRN3,Main,3826
     448
River Rch & RM=DRYRN3,Main,2773
     512
Boundary for River Rch & Prof#=DRYRN3,Main      ,1
Up Type=0
Dn Type=3
Dn Slope=0.050125

--- DRYRN3.g01 (geometry) ---

Geom Title=Geometry
Program Version=6.20

River Reach=DRYRN3          ,Main
Reach XY= 30
     2220784.557      626915.998      2220686.64      627080.581
     2220497.752      627120.859      2220361.64      627234.748
     2220310.946      627352.109     2220209.557      627386.831
     2220088.723      627545.1642219884.61339915627676.903424431
     2219764.418       627888.22     2219597.751      627945.859
     2219520.668      628101.414     2219307.154      628194.472
     2219228.307      628308.359     2219094.279      628393.081
     2219081.085      628596.553     2218697.057      628524.331
     2218627.613      628545.858     2218573.446      628618.775
     2218349.835      628683.359     2218189.418      628562.525
     2218107.473      628543.775     2217981.085      628676.414
     2217869.279      628697.942     2217158.428      628509.227
     2217020.408      628415.476     2216435.772        628471.9
2216134.05201962628681.831306522     2216148.316      628792.039
     2216030.087      628845.685     2215990.276      628940.715

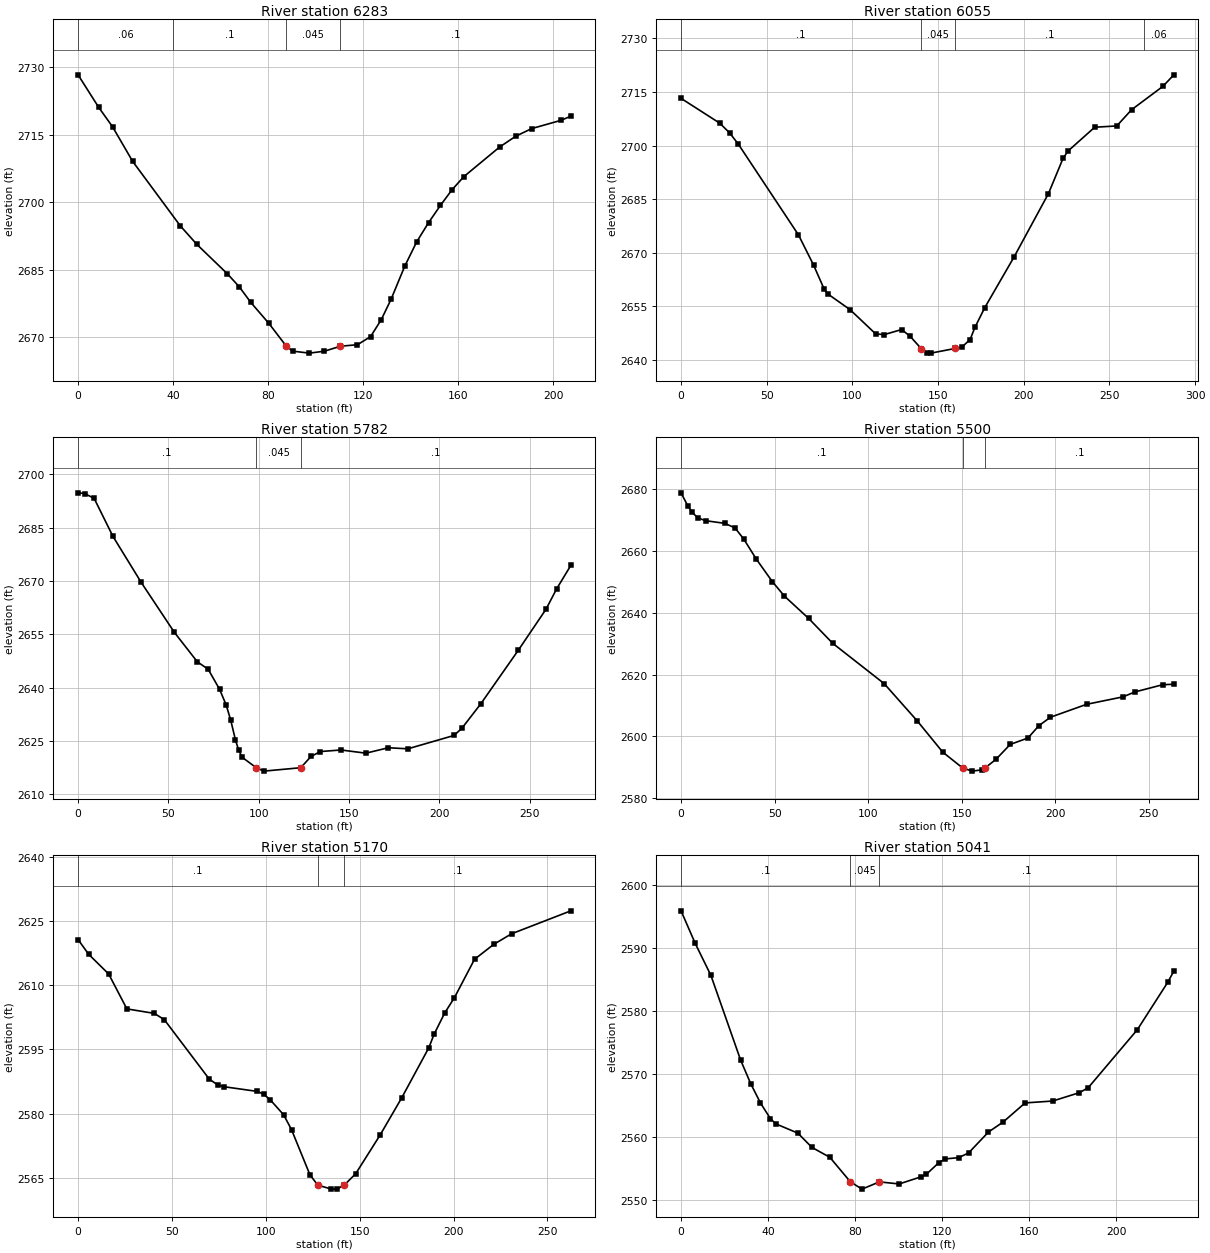
Type RM Length L Ch R = 1 ,6283    ,224.4,228.2,229.9
XS GIS Cut Line= 2
2220697.77104417 626859.355086852220864.28418442626983.018373274
#Sta/Elev= 30
       0  2728.3     8.7 2721.07    14.5 2716.78      23 2709.07      43 2694.79
      50 2690.65    62.8 2684.14    67.8 2681.27    72.7 2677.77    80.3 2673.12
    87.7 2668.02    90.3 2666.95    97.4 2666.51   103.7 2666.94   110.4 2668.04
   117.6 2668.38   123.1 2670.17   127.6 2673.93   131.7 2678.42   137.5 2685.82
   142.5  2691.2   147.5 2695.47   152.5  2699.3   157.4 2702.79   162.4 2705.71
   177.4 2712.26   184.2 2714.67   190.9 2716.36   203.2 2718.19   207.4 2719.11
#Mann= 4 ,-1,0
       0     .06       0      40      .1       0    87.7    .045       0
   110.4      .1       0
Bank Sta=87.7,110.4
XS Rating Curve= 0 ,0
Exp/Cntr=0.3,0.1

Type RM Length L Ch R = 1 ,6055    ,270,272.8,267.3
XS GIS Cut Line= 2
2220558.51480988626978.5653282192220731.99777921627207.901351084
#Sta/Elev= 30
       0 2713.24    22.6 2706.29    28.4 2703.54    33.4 2700.44    68.5 2675.03
    77.3 2666.61    83.5 2659.86    85.9  2658.4    98.6  2654.1   113.6 2647.29
   118.6 2647.11   128.7 2648.52   133.7 2646.63   140.1 2643.21   143.7 2641.93
   145.8 2641.92   160.1 2643.24   163.8 2643.57   168.7 2645.73   171.5 2649.12
   177.2 2654.61   194.4 2668.89   214.4 2686.57   222.9 2696.41   225.8 2698.48
   241.4 2705.16   254.3 2705.52   262.9 2710.05   281.2  2716.6   287.6 2719.83
#Mann= 4 ,-1,0
       0      .1       0   140.1    .045       0   160.1      .1       0
     270     .06       0
Bank Sta=140.1,160.1
XS Rating Curve= 0 ,0
Exp/Cntr(USF)=0,0
Exp/Cntr=0.3,0.1

Type RM Length L Ch R = 1 ,5782    ,281.3,282.1,278.2
XS GIS Cut Line= 2
2220341.93875027627114.3829772522220516.97443367627323.444157684
#Sta/Elev= 30
       0 2694.81     3.6 2694.62     8.9 2693.25    19.3 2682.56    34.9 2669.64
    53.3 2655.54      66 2647.27      72 2645.16    78.3 2639.54    81.9  2635.2
    84.5 2630.82    87.1 2625.26    88.8 2622.55    90.7 2620.43   98.68 2617.43
   102.8  2616.5  123.23 2617.46   128.9 2620.62   134.1 2622.01   145.5 2622.45
   159.3 2621.55   171.7 2623.08   182.5 2622.78     208 2626.53   212.3  2628.5
   222.8 2635.39   243.6  2650.5     259 2662.09   264.8 2667.76   272.7  2674.4
#Mann= 3 ,-1,0
       0      .1       0   98.68    .045       0  123.23      .1       0
Bank Sta=98.68,123.23
XS Rating Curve= 0 ,0
Exp/Cntr=0.3,0.1

Type RM Length L Ch R = 1 ,5500    ,327.8,329.7,329.3
XS GIS Cut Line= 2
2220129.97245531627254.8887633012220293.02990195627461.873941171
#Sta/Elev= 30
       0 2678.86     3.6 2674.62       6 2672.51     8.9 2670.78    13.1 2669.83
    23.3 2668.98    28.8 2667.52    33.5 2663.91    40.2 2657.42    48.8 2650.09
    55.3 2645.38    68.2 2638.18    81.1  2630.1   108.6 2617.05   126.4 2604.89
   139.9 2594.87   150.6  2589.7   155.7  2588.7   160.8 2589.11   162.7  2589.8
   168.4 2592.53     176 2597.35   185.5 2599.43   191.3 2603.41   197.5 2606.16
   216.8 2610.34   236.3 2612.76   242.7 2614.36   257.5 2616.69   263.5 2616.85
#Mann= 3 ,-1,0
       0      .1       0   150.6    .045       0   162.7      .1       0
Bank Sta=150.6,162.7
XS Rating Curve= 0 ,0
Exp/Cntr(USF)=0,0
Exp/Cntr=0.3,0.1

Type RM Length L Ch R = 1 ,5170    ,127.5,129.1,129.3
XS GIS Cut Line= 3
2219921.58294846627495.8333184112220044.32338763627672.101123807
2220091.36024604627679.842158877
#Sta/Elev= 30
       0 2620.64     5.7 2617.18    16.3 2612.61      26 2604.47    40.6 2603.42
    45.9 2601.98    69.9 2588.09    74.5  2586.7    77.5 2586.33    95.5 2585.22
    99.1 2584.51   102.5  2583.2   109.5 2579.77   113.7 2576.31   123.5 2565.79
  127.67 2563.37     135 2562.43   137.9 2562.45   141.8 2563.37   147.9 2566.03
   160.9 2575.05   172.4 2583.72   186.9 2595.45   189.6 2598.51   195.3 2603.51
   200.5  2607.1   211.2 2616.04   221.4 2619.51   230.9 2621.98   262.5 2627.34
#Mann= 3 ,-1,0
       0      .1       0  127.67    .045       0   141.8      .1       0
Bank Sta=127.67,141.8
XS Rating Curve= 0 ,0
Exp/Cntr=0.3,0.1

Type RM Length L Ch R = 1 ,5041    ,105.2,102.1,99
XS GIS Cut Line= 3
2219851.35356846627597.1189707172219922.55816872627727.830272617
2219998.84881185627742.579796956
#Sta/Elev= 30
       0  2595.9     6.5 2590.74    13.7 2585.68    27.4 2572.22      32 2568.51
    36.5 2565.44    41.1 2562.94    43.5 2562.13    53.7 2560.65    60.2 2558.38
    68.4 2556.82   77.86 2552.93    83.2 2551.77    91.2 2552.92   100.3 2552.59
   110.4 2553.73   112.7 2554.09   118.6 2555.99   121.5 2556.56   127.6 2556.76
   132.2  2557.5   141.3 2560.81   148.2 2562.44   158.2 2565.44   170.9 2565.74
   183.1 2567.06   187.2 2567.84   209.8 2577.05   223.8 2584.57   226.6 2586.35
#Mann= 3 ,-1,0
       0      .1       0   77.86    .045       0    91.2      .1       0
Bank Sta=77.86,91.2
XS Rating Curve= 0 ,0
Exp/Cntr(USF)=0,0
Exp/Cntr=0.3,0.1

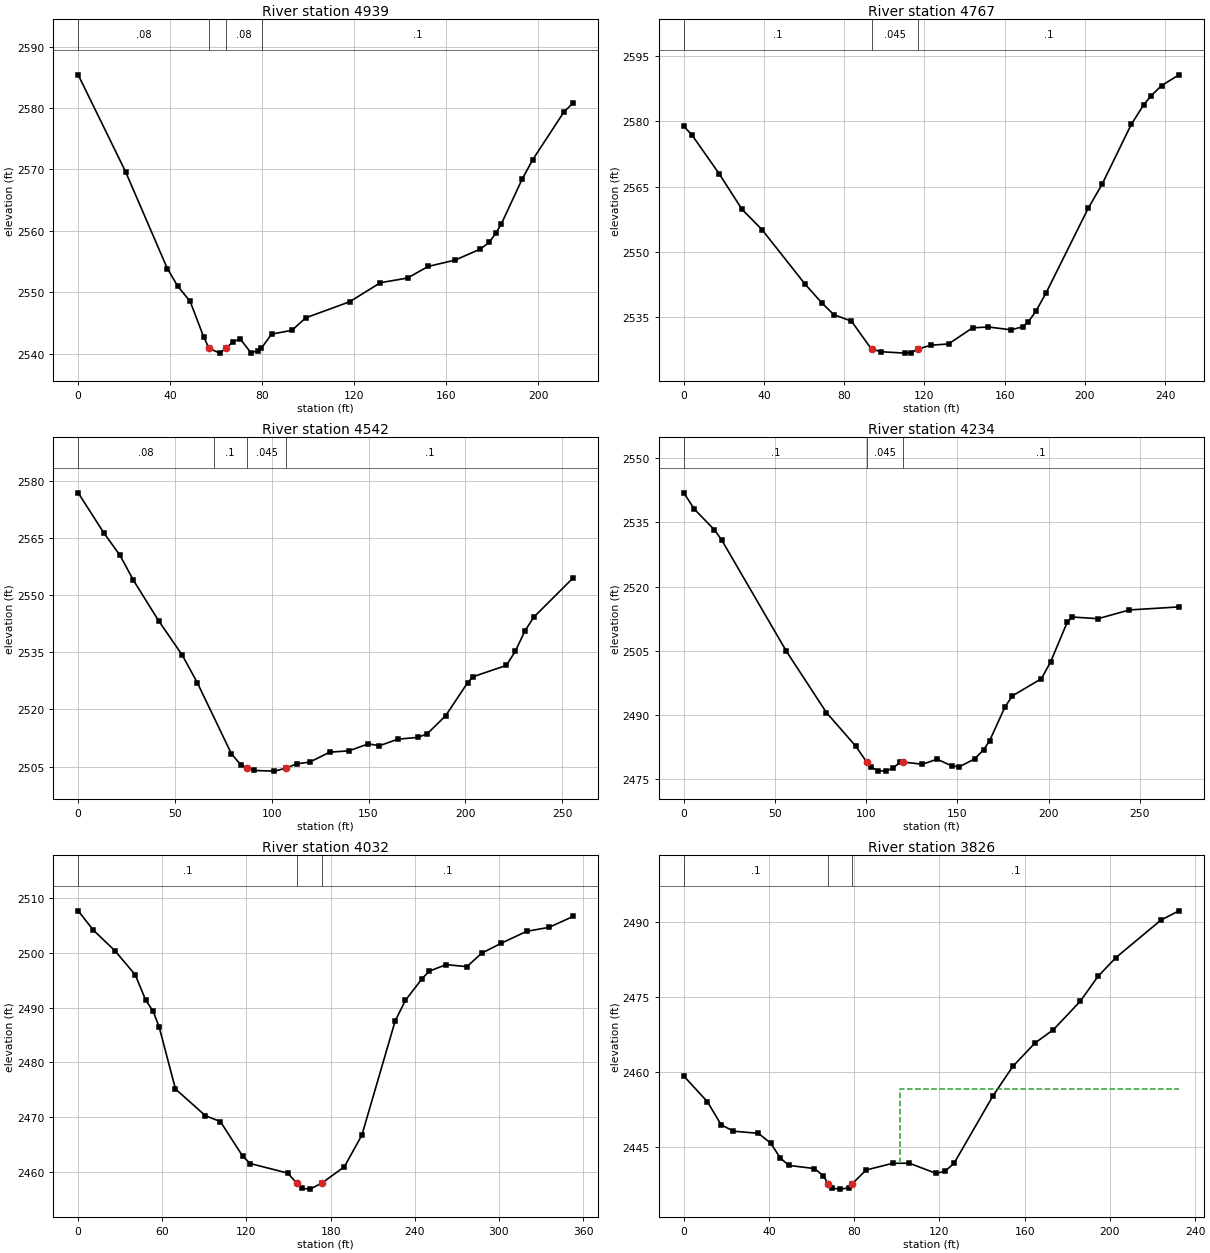
Type RM Length L Ch R = 1 ,4939    ,162,171.3,172.7
XS GIS Cut Line= 2
2219769.97905957627717.4883007252219959.79103278627819.083696077
#Sta/Elev= 30
       0  2585.4    20.6 2569.64    38.8 2553.85    43.3    2551    48.7 2548.52
    54.6 2542.72    56.9 2540.89    61.5 2540.11    64.3 2540.89    67.2 2541.93
    70.5 2542.42    75.1 2540.16    78.2 2540.52    79.6 2540.88    84.1  2543.2
      93 2543.83    98.9 2545.85     118 2548.46   131.4 2551.57   143.2 2552.33
   152.1 2554.21   163.9 2555.25   174.9 2557.05   178.7 2558.13   181.7 2559.69
     184 2561.14     193  2568.4   197.6 2571.57   211.2 2579.35   215.3 2580.86
#Mann= 4 ,-1,0
       0     .08       0    56.9    .045       0    64.3     .08       0
      80      .1       0
Bank Sta=56.9,64.3
XS Rating Curve= 0 ,0
Exp/Cntr(USF)=0,0
Exp/Cntr=0.3,0.1

Type RM Length L Ch R = 1 ,4767    ,226.5,225.3,222
XS GIS Cut Line= 3
2219690.98906197627801.7813831832219766.74468204627904.875832681
2219843.48841985627995.722564968
#Sta/Elev= 30
       0 2578.92     4.2  2576.8    17.6 2567.99      29 2559.78      39 2555.08
    60.5 2542.51    68.7 2538.27    74.8 2535.49    83.6    2534    93.6 2527.54
    98.5 2526.95   110.1 2526.63   113.4 2526.76   116.8 2527.58   123.3 2528.46
     132 2528.74     144 2532.46   151.9 2532.65   163.2    2532   168.9 2532.69
   171.7 2533.78   175.5 2536.24   180.7 2540.55   201.6 2559.96   208.6 2565.56
   223.1 2579.31   229.3 2583.85   233.1 2585.98   238.3 2588.29   246.9 2590.75
#Mann= 3 ,-1,0
       0      .1       0    93.6    .045       0   116.8      .1       0
Bank Sta=93.6,116.8
XS Rating Curve= 0 ,0
Exp/Cntr=0.3,0.1

Type RM Length L Ch R = 1 ,4542    ,294.5,308,310.8
XS GIS Cut Line= 2
2219485.61875276627925.4847051392219687.87450725628082.042506726
#Sta/Elev= 30
       0 2576.84    13.3 2566.29    21.6 2560.44    28.5 2553.94    41.5 2543.33
    53.8 2534.23    61.5 2527.08    79.1 2508.44    84.2 2505.35    87.1 2504.66
      91    2504   101.4 2503.83  107.512504.638   112.8 2505.74   119.6 2506.19
   129.9  2508.8   139.8 2509.15   149.9 2510.98   155.6 2510.49   165.1  2512.2
   175.5 2512.69   180.3 2513.62   189.8 2518.34   201.2 2527.03     204  2528.6
   221.2 2531.57   225.8 2535.26   230.9 2540.72   235.4 2544.24   255.8 2554.58
#Mann= 4 ,-1,0
       0     .08       0      70      .1       0    87.1    .045       0
  107.51      .1       0
Bank Sta=87.1,107.51
XS Rating Curve= 0 ,0
Exp/Cntr(USF)=0,0
Exp/Cntr=0.3,0.1

Type RM Length L Ch R = 1 ,4234    ,211.6,201.7,200.2
XS GIS Cut Line= 4
2219319.74750834628070.0372951252219352.17539897628140.655529513
 2219364.2271504628221.4056957282219449.84480842628293.815141371
#Sta/Elev= 30
       0 2541.86     5.7 2538.09    16.7 2533.27    20.8 2530.83    56.3 2504.86
    78.2 2490.59    94.4  2482.7   100.3 2479.01   102.5 2477.89   106.3 2477.03
   110.6 2476.92   114.6 2477.59   118.7 2479.02   120.4 2479.04   130.8 2478.52
   138.9  2479.7     147 2478.13     151 2477.93   159.4 2479.75   164.5 2481.96
   167.7 2484.04   176.2 2491.97   180.2 2494.49   196.1 2498.49   201.2 2502.48
   210.2 2511.63   213.1 2512.88   227.1 2512.49   244.3 2514.53   271.5 2515.24
#Mann= 3 ,-1,0
       0      .1       0   100.3    .045       0   120.4      .1       0
Bank Sta=100.3,120.4
XS Rating Curve= 0 ,0
Exp/Cntr=0.3,0.1

Type RM Length L Ch R = 1 ,4032    ,211.3,206.6,203.4
XS GIS Cut Line= 2
2219110.85668556628189.0417626022219344.04788552628454.202723848
#Sta/Elev= 30
       0 2507.73    10.8  2504.2    26.2 2500.44    40.7 2496.02    48.1 2491.43
    53.5 2489.33    57.7 2486.53    69.4 2475.14    90.7 2470.26   101.4 2469.19
   117.4 2462.82   122.7 2461.51   149.3 2459.77   155.8 2457.96   159.7 2456.96
   165.4 2456.83   173.9 2457.96   189.8 2460.92   202.3  2466.7   226.1 2487.63
   233.4 2491.37   245.2 2495.32   250.4  2496.7   262.4 2497.89   277.2 2497.52
   287.8 2499.99   301.5 2501.78   319.8 2503.98   335.8 2504.71   353.1 2506.72
#Mann= 3 ,-1,0
       0      .1       0   155.8    .045       0   173.9      .1       0
Bank Sta=155.8,173.9
XS Rating Curve= 0 ,0
Exp/Cntr(USF)=0,0
Exp/Cntr=0.3,0.1

Type RM Length L Ch R = 1 ,3826    ,229.1,240.3,256.6
XS GIS Cut Line= 4
2219020.21492691628413.5104070122219049.11413315628444.243511361
2219107.54493197628449.9573863952219232.21750669628491.693711384
#Sta/Elev= 30
       0 2459.22    11.1 2454.07    17.5 2449.47    23.3 2448.17      35 2447.75
    40.8 2445.77    45.3  2442.8    49.3 2441.32    61.3 2440.69    65.4 2439.28
    67.8 2437.64    69.4 2436.75    73.4 2436.57    77.4 2436.81      792437.606
    85.5 2440.39      98 2441.74   105.8 2441.77   118.4 2439.72   122.7 2440.17
   126.9 2441.79     145 2455.17   154.5 2461.19   164.8 2465.82   173.5 2468.52
   186.1 2474.21   194.4 2479.18   202.8 2482.94   223.9 2490.44   232.4 2492.31
#Mann= 3 ,-1,0
       0      .1       0    67.8    .045       0      79      .1       0
#XS Ineff= 2 , 0
                          101.26         2456.61
Permanent Ineff=
       F       F
Bank Sta=67.8,79
XS Rating Curve= 0 ,0
Exp/Cntr=0.3,0.1

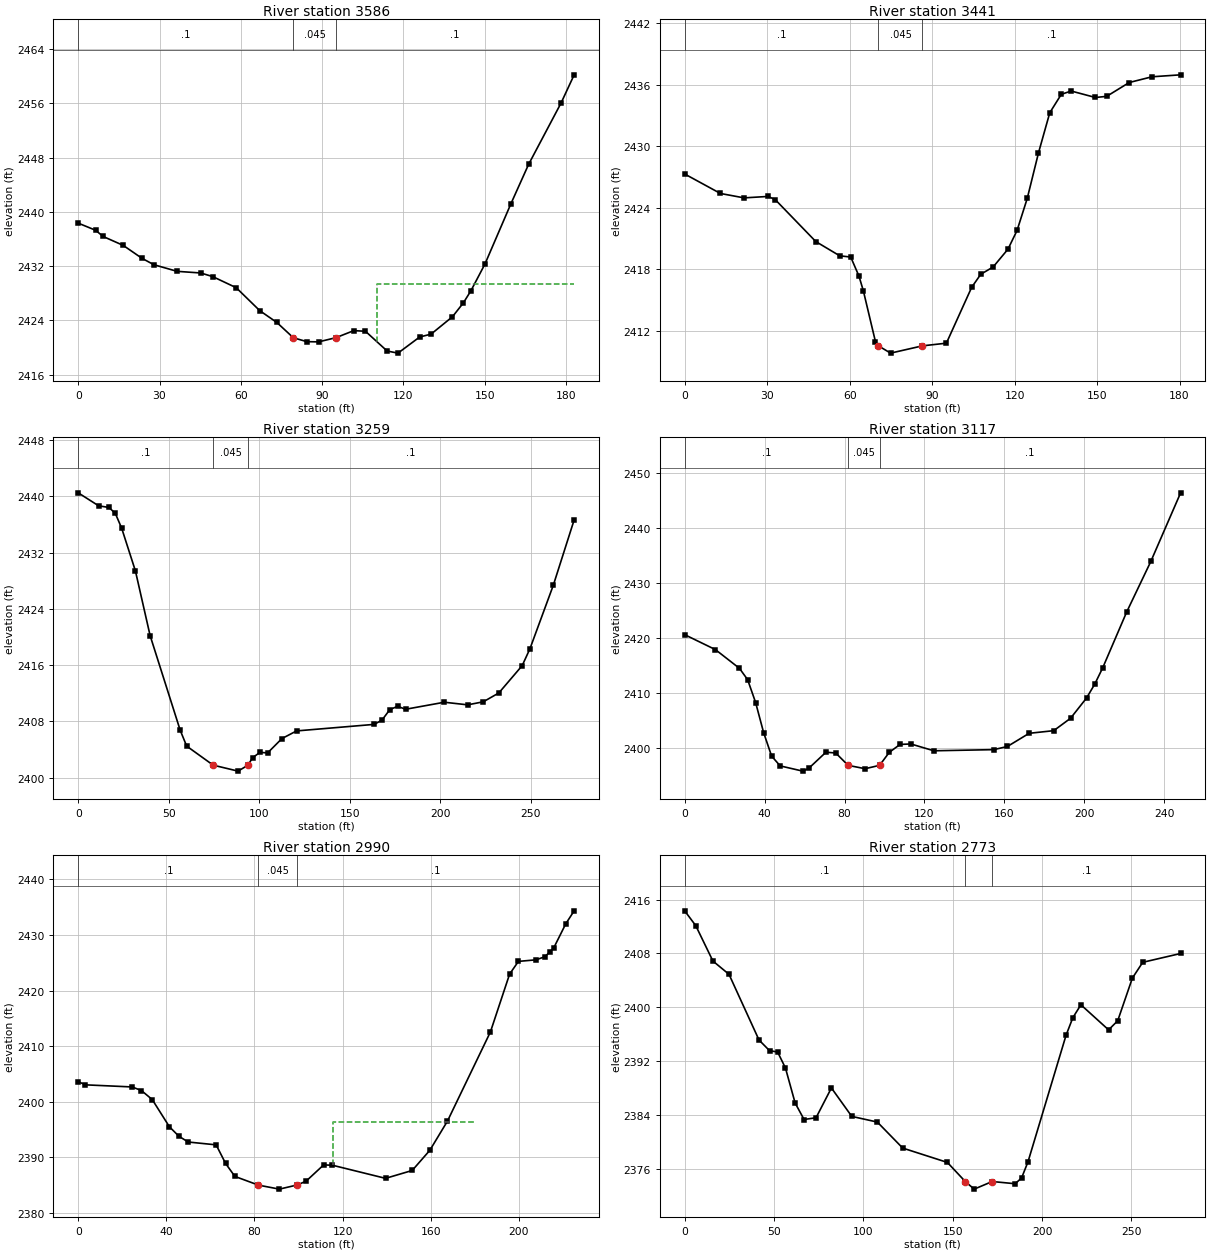
Type RM Length L Ch R = 1 ,3586    ,143,145,146.5
XS GIS Cut Line= 3
2219034.66341107628503.5413019682218993.80274863628599.713348919
2219000.77895929628677.946568459
#Sta/Elev= 30
       0 2438.35     6.4  2437.3     9.2 2436.38    16.6 2435.07    23.5 2433.17
    27.9 2432.22    36.5 2431.24    45.2    2431    49.6 2430.47    58.3 2428.83
      67 2425.44    73.3  2423.7    79.4 2421.44    84.4 2420.87    88.7 2420.84
   95.11 2421.46   101.7  2422.5     106  2422.4     114 2419.49     118 2419.18
     126 2421.56   130.2 2421.98   138.1 2424.55   142.1 2426.58   144.9 2428.37
   150.1 2432.33   159.6 2441.15   166.2 2447.02   178.2 2456.09     183 2460.22
#Mann= 3 ,-1,0
       0      .1       0    79.4    .045       0   95.11      .1       0
#XS Ineff= 2 , 0
                          110.38         2429.31
Permanent Ineff=
       F       F
Bank Sta=79.4,95.11
XS Rating Curve= 0 ,0
Exp/Cntr(USF)=0,0
Exp/Cntr=0.3,0.1

Type RM Length L Ch R = 1 ,3441    ,188.5,181.9,174.5
XS GIS Cut Line= 4
2218907.26711465628481.2188433772218881.37160801628542.911079786
 2218862.3307943628567.283321331 2218841.7667155628647.254738898
#Sta/Elev= 30
       0 2427.28      13 2425.38    21.6 2424.95    30.3 2425.09    32.9 2424.79
    47.7 2420.69    56.4  2419.3    60.4 2419.18    63.4 2417.32      65 2415.88
    69.4 2410.92   70.47 2410.52    74.9 2409.81    86.5 2410.52    95.2 2410.78
   104.4 2416.23   107.7  2417.5   112.2 2418.21   117.6 2419.95   120.9 2421.77
   124.6 2424.89   128.7 2429.34   132.8 2433.25     137 2435.05   140.6 2435.37
   149.4 2434.74   153.5 2434.85   161.7  2436.2     170 2436.76   180.4 2436.95
#Mann= 3 ,-1,0
       0      .1       0   70.47    .045       0    86.5      .1       0
Bank Sta=70.47,86.5
XS Rating Curve= 0 ,0
Exp/Cntr(USF)=0,0
Exp/Cntr=0.3,0.1

Type RM Length L Ch R = 1 ,3259    ,148.6,142,138
XS GIS Cut Line= 3
2218684.00378754628437.972025611     2218702.806628559.142321214
2218758.21965286628699.859482135
#Sta/Elev= 30
       0 2440.51    11.3 2438.66      17 2438.43    20.5 2437.58      24 2435.48
    31.6 2429.39    39.7 2420.21    56.3 2406.75    59.9 2404.48   74.54 2401.77
    88.3 2400.92   93.75 2401.77    96.3 2402.83   100.4 2403.59   104.6 2403.51
   112.5 2405.55   120.6 2406.64   163.5 2407.57   167.8 2408.19   172.1 2409.67
   176.4 2410.14   180.8 2409.72   202.2 2410.72   215.1 2410.35   223.7 2410.78
   232.3 2412.04   245.2 2415.93   249.5 2418.34   262.4 2427.37   273.9 2436.66
#Mann= 3 ,-1,0
       0      .1       0   74.54    .045       0   93.75      .1       0
Bank Sta=74.54,93.75
XS Rating Curve= 0 ,0
Exp/Cntr=0.3,0.1

Type RM Length L Ch R = 1 ,3117    ,120,126.3,130.3
XS GIS Cut Line= 4
2218558.52017629628525.8326752712218562.23147181628569.440397655
2218660.58080314628679.3875274942218666.61165836628735.984784205
#Sta/Elev= 30
       0 2420.61    15.4 2417.89    27.4 2414.49    31.5 2412.43    35.5 2408.27
    39.5 2402.81    43.5 2398.53    47.8 2396.74    59.1 2395.79      62 2396.27
    70.7 2399.23    75.6 2399.09    81.8 2396.84    90.3 2396.23   97.552396.843
   102.4 2399.21   107.8 2400.65   113.2 2400.73   124.7 2399.49   154.7  2399.7
   161.5 2400.27   172.4 2402.67   184.7 2403.15   193.1  2405.4   201.1 2409.08
   205.2  2411.6   209.2 2414.57   221.2 2424.73   233.3 2433.94   248.2 2446.41
#Mann= 3 ,-1,0
       0      .1       0    81.8    .045       0   97.55      .1       0
Bank Sta=81.8,97.55
XS Rating Curve= 0 ,0
Exp/Cntr(USF)=0,0
Exp/Cntr=0.3,0.1

Type RM Length L Ch R = 1 ,2990    ,210.9,217.3,221.8
XS GIS Cut Line= 3
2218448.45307063628542.1085410492218472.82531217628611.417102941
2218487.07066169628762.380196303
#Sta/Elev= 30
       0  2403.6     3.3 2403.03    24.5 2402.65    28.7    2402    33.6 2400.38
    41.4 2395.48    45.7 2393.78    49.9 2392.74    62.6 2392.23    66.9 2388.88
    71.1 2386.55    81.8 2384.98    91.3 2384.26    99.3    2385   103.4 2385.68
   111.4 2388.62   115.4 2388.56   139.5  2386.2   151.6 2387.62   159.6 2391.25
   167.6 2396.51   187.1 2412.56   195.8 2422.96   199.8 2425.25   207.8 2425.53
   211.8 2426.09     214 2426.92   215.9 2427.73   221.3 2432.02   225.1 2434.35
#Mann= 3 ,-1,0
       0      .1       0    81.8    .045       0    99.3      .1       0
#XS Ineff= 1 ,-1
  115.52   179.6 2396.42
Permanent Ineff=
       F
Bank Sta=81.8,99.3
XS Rating Curve= 0 ,0
Exp/Cntr(USF)=0,0
Exp/Cntr=0.3,0.1

Type RM Length L Ch R = 1 ,2773    ,303.1,293.6,281.4
XS GIS Cut Line= 3
2218386.59633548628499.2736612332218360.83275206628547.613101935
 2218226.5232122628725.296599586
#Sta/Elev= 30
       0 2414.32     6.2 2412.12    15.8 2406.87    24.8  2404.9    41.6 2395.15
    47.5 2393.57      52 2393.38    56.4 2390.99    61.8 2385.81    66.8 2383.36
    73.5 2383.62    82.1 2388.04    93.5 2383.82   107.8 2382.98     122 2379.12
     147 2376.99     157 2374.16     162 2373.03   172.1 2374.16   184.9 2373.83
   188.5 2374.68   192.1 2377.08   213.4 2395.86   217.2 2398.47   221.7 2400.38
   237.2 2396.66   242.3 2398.01   250.5 2404.34   256.3 2406.68   277.5 2407.99
#Mann= 3 ,-1,0
       0      .1       0     157    .045       0   172.1      .1       0
Bank Sta=157,172.1
XS Rating Curve= 0 ,0
Exp/Cntr=0.3,0.1

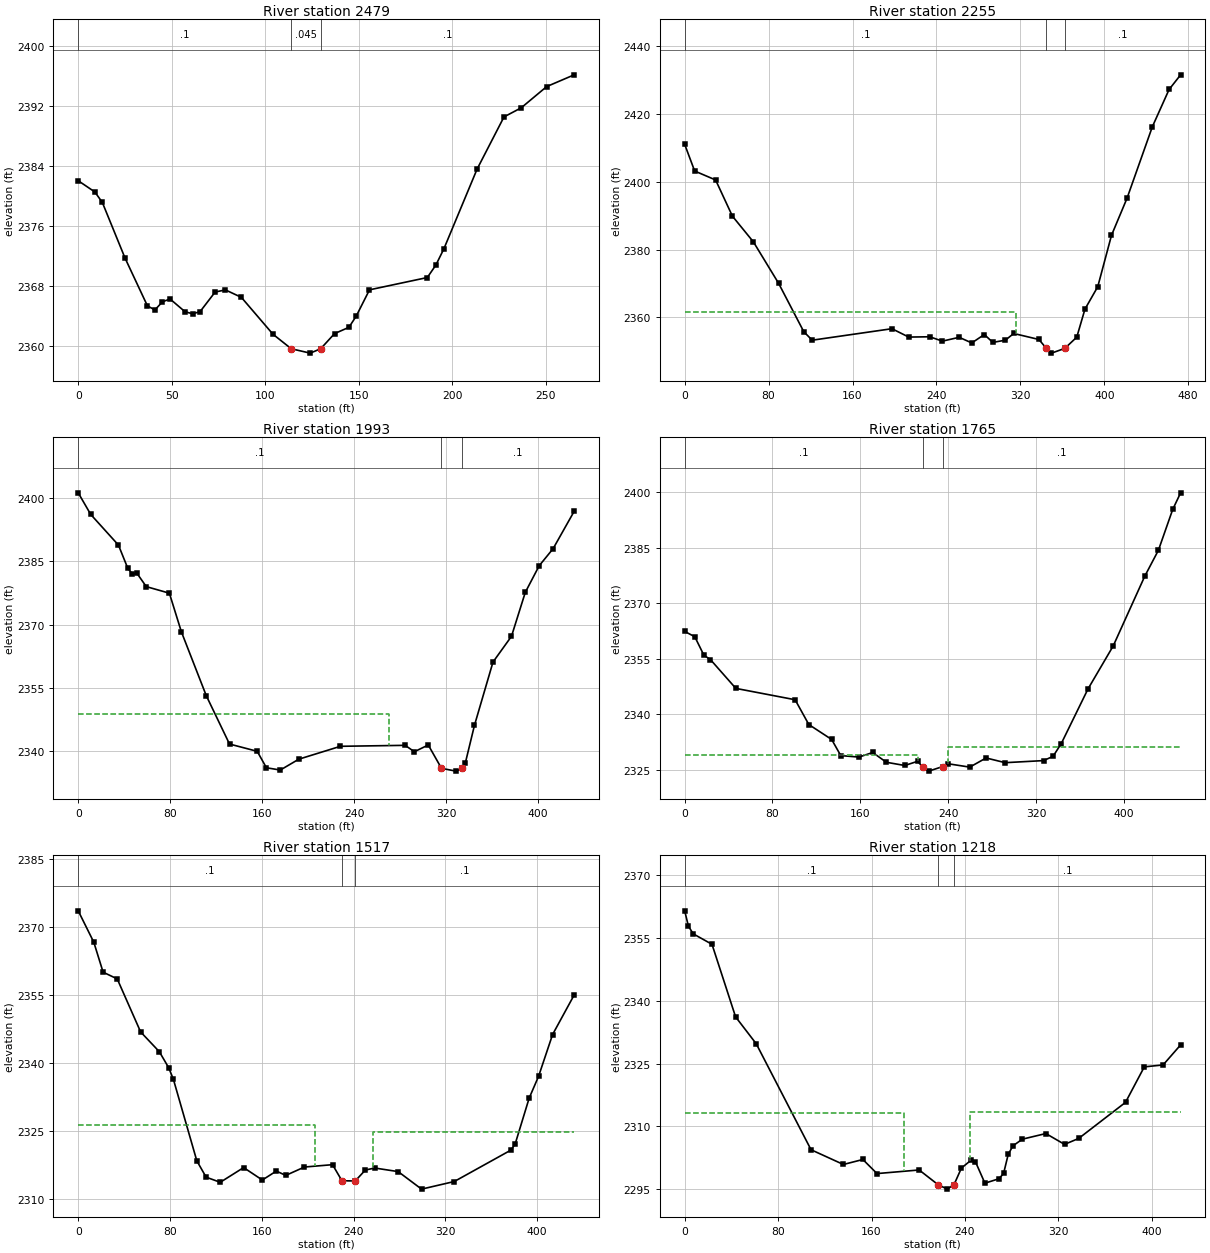
Type RM Length L Ch R = 1 ,2479    ,217.8,224.8,230.3
XS GIS Cut Line= 4
2218013.64688265628484.3490875392218020.96022673628558.527291828
2218090.95937726628631.6607326762218133.79467833628710.017990727
#Sta/Elev= 30
       0    2382     8.9  2380.5    12.9  2379.1      25  2371.7      37 2365.31
      41 2364.77      45 2365.85    49.1 2366.23    57.1 2364.53    61.1 2364.26
    65.1 2364.53    73.2 2367.16    78.7 2367.44    87.2 2366.45   104.1 2361.53
   113.9 2359.59     124 2359.01   129.6 2359.59     137 2361.61   144.7 2362.45
   148.6 2363.94   155.7 2367.45   186.6 2369.09   191.2 2370.76   195.5 2372.94
   213.2 2383.54   227.6 2390.51   236.8 2391.72   250.4 2394.55   265.1 2396.12
#Mann= 3 ,-1,0
       0      .1       0   113.9    .045       0   129.6      .1       0
Bank Sta=113.9,129.6
XS Rating Curve= 0 ,0
Exp/Cntr(USF)=0,0
Exp/Cntr=0.3,0.1

Type RM Length L Ch R = 1 ,2255    ,260.4,262,263.1
XS GIS Cut Line= 2
2217857.45960555628343.7102144642217875.83584291628816.177372008
#Sta/Elev= 30
       0 2411.09     9.5 2403.21    29.5 2400.56    45.5 2389.88    65.5 2382.28
    89.5 2370.07   113.6 2355.73   121.6 2353.25   197.6 2356.64   213.6 2354.17
   233.6 2354.26   245.7 2352.97   261.7  2354.1   273.7 2352.44   285.7 2354.93
   293.7  2352.6   305.7 2353.25   313.7 2355.23   337.7 2353.46   344.4 2350.99
   349.7 2349.43   362.4 2350.83   373.8 2354.15   381.6 2362.42   393.8 2369.04
   406.9 2384.22   421.8 2395.24   445.8 2416.24   461.8 2427.28   472.8 2431.61
#Mann= 3 ,-1,0
       0      .1       0   344.4    .045       0   362.4      .1       0
#XS Ineff= 2 , 0
          315.52 2361.45
Permanent Ineff=
       F       F
Bank Sta=344.4,362.4
XS Rating Curve= 0 ,0
Exp/Cntr=0.3,0.1

Type RM Length L Ch R = 1 ,1993    ,224.1,227.2,229.5
XS GIS Cut Line= 2
2217659.88450191628302.339583884 2217615.0328074628731.392586072
#Sta/Elev= 30
       0  2401.3    10.9 2396.16      35 2388.88    43.1 2383.38    47.1    2382
    51.1 2382.17    59.2 2379.01    79.3 2377.45    89.7  2368.3   111.4 2353.09
   131.6  2341.6   155.7 2339.87   163.7 2335.96   175.8 2335.42   191.9    2338
   228.1 2341.06   284.4 2341.29   292.4 2339.77   304.5 2341.37     3162335.823
   328.6 2335.16   333.7 2335.81   336.7 2337.05   344.7 2346.06   360.8 2361.08
   376.9 2367.21   388.9 2377.65     401 2383.98   413.1 2388.03   431.4  2396.9
#Mann= 3 ,-1,0
       0      .1       0     316    .045       0   333.7      .1       0
#XS Ineff= 2 , 0
           270.4 2348.82
Permanent Ineff=
       F       F
Bank Sta=316,333.7
XS Rating Curve= 0 ,0
Exp/Cntr(USF)=0,0
Exp/Cntr=0.3,0.1

Type RM Length L Ch R = 1 ,1765    ,249.9,248.3,246.1
XS GIS Cut Line= 3
2217482.55265001628348.3552179232217428.64079375628539.120451903
2217327.76805375628771.709440896
#Sta/Elev= 30
       0 2362.41     9.2 2360.98    17.5    2356    23.5  2354.8    46.6 2347.04
   100.6 2343.98   113.1 2337.29   133.9 2333.26   142.2 2328.91   158.8 2328.51
   171.3 2329.75   183.7 2327.11   200.5 2326.24   212.3 2327.38   216.7 2325.83
   222.3 2324.72   234.92325.935   239.7 2326.72   259.7  2325.8   274.6 2328.27
     292    2327   326.9 2327.56   335.6 2328.71   343.1 2332.17   367.4 2346.88
   390.4  2358.5   419.1 2377.28   431.6 2384.33   444.6 2395.32   451.8  2399.8
#Mann= 3 ,-1,0
       0      .1       0   216.7    .045       0   234.9      .1       0
#XS Ineff= 2 , 0
          212.38 2329.12  239.71         2331.24
Permanent Ineff=
       F       F
Bank Sta=216.7,234.9
XS Rating Curve= 0 ,0
Exp/Cntr=0.3,0.1

Type RM Length L Ch R = 1 ,1517    ,299.7,299.3,295.4
XS GIS Cut Line= 2
2217223.54443062628279.8749514572217137.64165883628703.584569069
#Sta/Elev= 30
       0 2373.55    13.6 2366.61    21.7    2360      34 2358.52    54.4 2346.81
    70.7 2342.44    78.9 2338.89      83 2336.31   103.4 2318.33   111.5 2314.73
   123.8  2313.6   144.2 2316.85   160.5  2314.1   172.7 2316.08   180.9 2315.12
   197.2 2316.97   221.7 2317.49   229.9 2313.93   241.5  2313.9   250.3 2316.31
   258.5 2316.75   278.9 2315.96   299.3 2312.09   327.8 2313.77   377.2 2320.71
   380.9 2322.08   393.1  2332.2   401.3 2337.01   413.5 2346.23   432.3 2354.96
#Mann= 3 ,-1,0
       0      .1       0   229.9    .045       0   241.5      .1       0
#XS Ineff= 2 , 0
          206.38  2326.2  256.71         2324.75
Permanent Ineff=
       F       F
Bank Sta=229.9,241.5
XS Rating Curve= 0 ,0
Exp/Cntr(USF)=0,0
Exp/Cntr=0.3,0.1

Type RM Length L Ch R = 1 ,1218    ,283.9,284.3,284.1
XS GIS Cut Line= 3
2216926.13180609628205.9909547732216904.24112576  628364.6573259
2216927.46356195628628.211146728
#Sta/Elev= 30
       0 2361.43     3.2 2357.77     7.3 2355.94    23.4 2353.44    43.6 2336.13
    61.3  2329.7   108.2 2304.43   135.9 2300.91   152.6  2302.1   164.7 2298.74
   200.8  2299.6   216.9 2296.11   224.9 2295.03   230.7 2296.12     237 2300.06
     245 2301.88     249 2301.56   257.1 2296.45   269.1  2297.5   273.1 2298.77
   277.1 2303.37   281.2 2305.38   289.2 2306.95   309.3 2308.29   325.3 2305.71
   337.4 2307.12   377.5 2315.73   393.6  2324.2   409.7 2324.66   424.7 2329.44
#Mann= 3 ,-1,0
       0      .1       0   216.9    .045       0   230.7      .1       0
#XS Ineff= 2 , 0
          187.92 2313.14  244.41         2313.47
Permanent Ineff=
       F       F
Bank Sta=216.9,230.7
XS Rating Curve= 0 ,0
Exp/Cntr=0.3,0.1

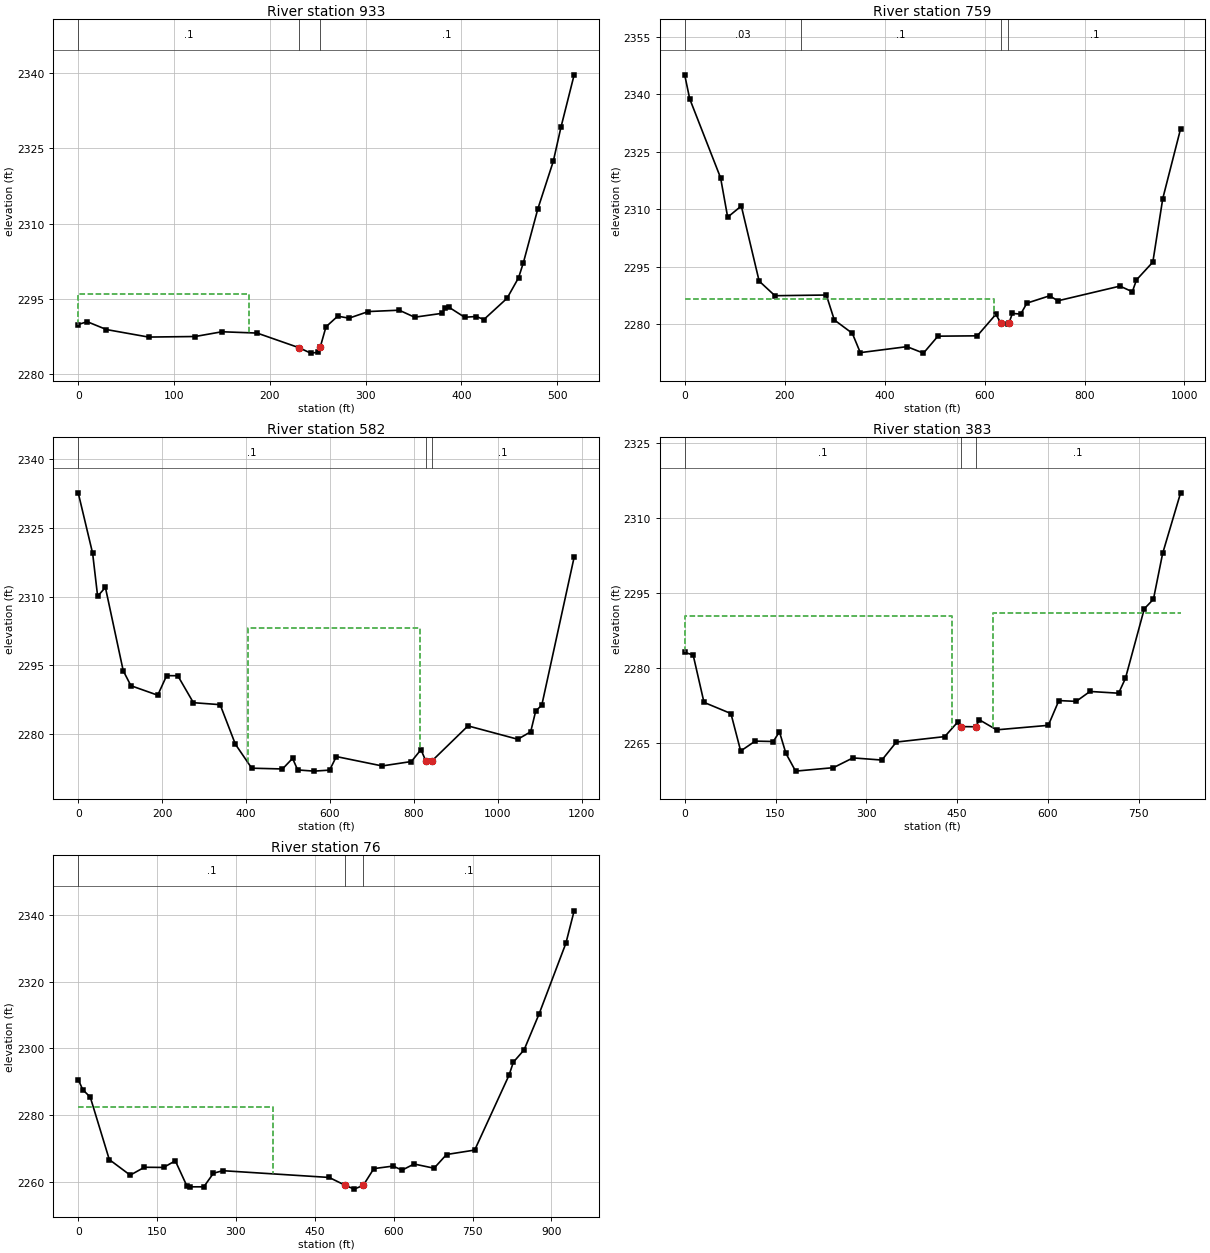
Type RM Length L Ch R = 1 ,933     ,175.7,174.9,173
XS GIS Cut Line= 2
2216605.30050191 628219.81453398  2216656.414077 628734.88209832
#Sta/Elev= 30
       0 2289.82     9.4 2290.38    29.5 2288.81    73.4 2287.31     122 2287.42
     150 2288.37   186.7 2288.11   230.5 2285.18   242.6  2284.1   250.6 2284.27
   252.5 2285.24   258.6 2289.36   270.8 2291.48   282.7 2291.09   302.8 2292.41
     335 2292.68   351.1 2291.28   379.2 2292.04   383.2 2293.05   387.3 2293.23
   403.3 2291.27   415.4 2291.42   423.4 2290.82   447.6 2295.07   459.6 2299.17
   464.6 2302.17   479.7 2312.93   495.8 2322.42   503.8 2329.22   517.6 2339.72
#Mann= 3 ,-1,0
       0      .1       0   230.5    .045       0   252.5      .1       0
#XS Ineff= 2 , 0
          178.48 2295.98
Permanent Ineff=
       F       F
Bank Sta=230.5,252.5
XS Rating Curve= 0 ,0
Exp/Cntr(USF)=0,0
Exp/Cntr=0.3,0.1

Type RM Length L Ch R = 1 ,759     ,178.3,176.7,172.7
XS GIS Cut Line= 4
2216558.79631097627901.6614507362216391.69469298628104.972285128
2216397.01082977628250.3564139392216546.41974156628814.571646632
#Sta/Elev= 30
       0 2345.08      10 2338.83    71.9 2318.15      86 2307.89   113.3 2310.81
     149 2291.19   180.6 2287.37   283.4 2287.55   299.4 2281.04   335.4 2277.55
   351.4  2272.5   444.7 2274.06   477.8 2272.37   506.7  2276.8   585.4 2276.89
   622.6  2282.5632.75542280.188   647.4 2279.95649.05542280.301   655.7 2282.75
   672.3 2282.56   684.7 2285.43   730.2 2287.35   746.7 2286.04   870.9 2289.88
   895.7 2288.41     904 2291.51   936.7 2296.15   956.6 2312.76   992.3 2331.01
#Mann= 4 ,-1,0
       0     .03       0   233.5      .1       0632.7554    .045       0
   647.4      .1       0
#XS Ineff= 2 , 0
          619.74 2286.49
Permanent Ineff=
       T       F
Bank Sta=632.7554,649.0554
XS Rating Curve= 0 ,0
Exp/Cntr(USF)=0,0
Exp/Cntr=0.3,0.1

Type RM Length L Ch R = 1 ,582     ,200.8,198.8,196.3
XS GIS Cut Line= 5
2216518.83973338627838.4504755152216263.26265553628130.658692617
2216237.49852992628454.5642646892216344.55453681628602.894876643
2216463.21902637628863.440821119
#Sta/Elev= 30
       0 2332.58    34.4  2319.4    46.3 2310.06    64.8    2312   107.3 2293.85
   125.6 2290.59   189.6 2288.52   210.8 2292.78   237.4 2292.76   274.6 2286.89
   338.4 2286.46   374.7 2277.85   413.7 2272.63     487 2272.46   511.1 2274.77
   523.2 2272.25     562 2271.99   599.4 2272.21   615.4 2275.16   724.5 2273.12
   794.3 2274.08   817.2 2276.67  828.622274.217  843.422274.215   929.3 2281.84
    1048 2278.93  1078.8 2280.56  1090.8  2285.1  1105.2 2286.33  1182.4 2318.58
#Mann= 3 ,-1,0
       0      .1       0  828.62    .045       0  843.42      .1       0
#XS Ineff= 1 ,-1
  405.18  815.892303.079
Permanent Ineff=
       T
Bank Sta=828.62,843.42
XS Rating Curve= 0 ,0
Exp/Cntr(USF)=0,0
Exp/Cntr=0.3,0.1

Type RM Length L Ch R = 1 ,383     ,301.2,307.3,299.9
XS GIS Cut Line= 3
  2215747.553704628446.1411098582216097.48510268628617.174995727
 2216404.1665532628917.958726047
#Sta/Elev= 30
       0 2283.15      14 2282.63    31.9 2273.17    76.4 2270.94    92.5 2263.46
   116.4 2265.44   146.3 2265.36   156.5  2267.3   167.2 2262.99   183.2 2259.45
   245.6 2260.14   277.9 2262.09   325.7 2261.66   349.6 2265.25   429.5 2266.34
   450.8 2269.22   456.5 2268.34   480.9  2268.3   486.6  2269.7   515.2 2267.69
   600.6 2268.59     618 2273.53   646.6 2273.37   669.4 2275.35   716.7    2275
     728 2277.98   759.1 2291.85   774.2 2293.75   789.4 2302.89   819.1 2314.99
#Mann= 3 ,-1,0
       0      .1       0   456.5    .045       0   480.9      .1       0
#XS Ineff= 2 , 0
        441.7128 2290.39  510.02         2290.98
Permanent Ineff=
       F       F
Bank Sta=456.5,480.9
XS Rating Curve= 0 ,0
Exp/Cntr(USF)=0,0
Exp/Cntr=0.3,0.1

Type RM Length L Ch R = 1 ,76      ,,,
XS GIS Cut Line= 5
2215692.55170384628517.7882346792215946.88731485628650.785184242
2215973.05136751628835.071120359  2216054.956228628905.600305786
 2216409.4346254628978.515643802
#Sta/Elev= 30
       0 2290.64     8.6 2287.61   22.98 2285.34   59.11 2266.64   98.88 2261.97
  125.96 2264.34  162.29 2264.28  184.64 2266.27  206.75  2258.7  211.73 2258.47
  238.81 2258.47  257.13 2262.54  274.91 2263.31  477.27 2261.28  508.05  2258.9
  524.77 2257.78  542.09 2258.91   562.2 2263.93  598.81 2264.69  615.78 2263.47
   638.7 2265.31  676.74 2264.05  700.45 2268.16  753.99 2269.49  819.33 2291.95
   827.5 2295.84  847.92 2299.53   876.5 2310.32  927.38 2331.48  943.13 2341.22
#Mann= 3 ,-1,0
       0      .1       0  508.05    .045       0  542.09      .1       0
#XS Ineff= 2 , 0
          369.76 2282.43
Permanent Ineff=
       F       F
Bank Sta=508.05,542.09
XS Rating Curve= 0 ,0
Exp/Cntr(USF)=0,0
Exp/Cntr=0.3,0.1
LCMann Table=0

Chan Stop Cuts=-1
Use User Specified Reach Order=0
Composite Channel Slope=5